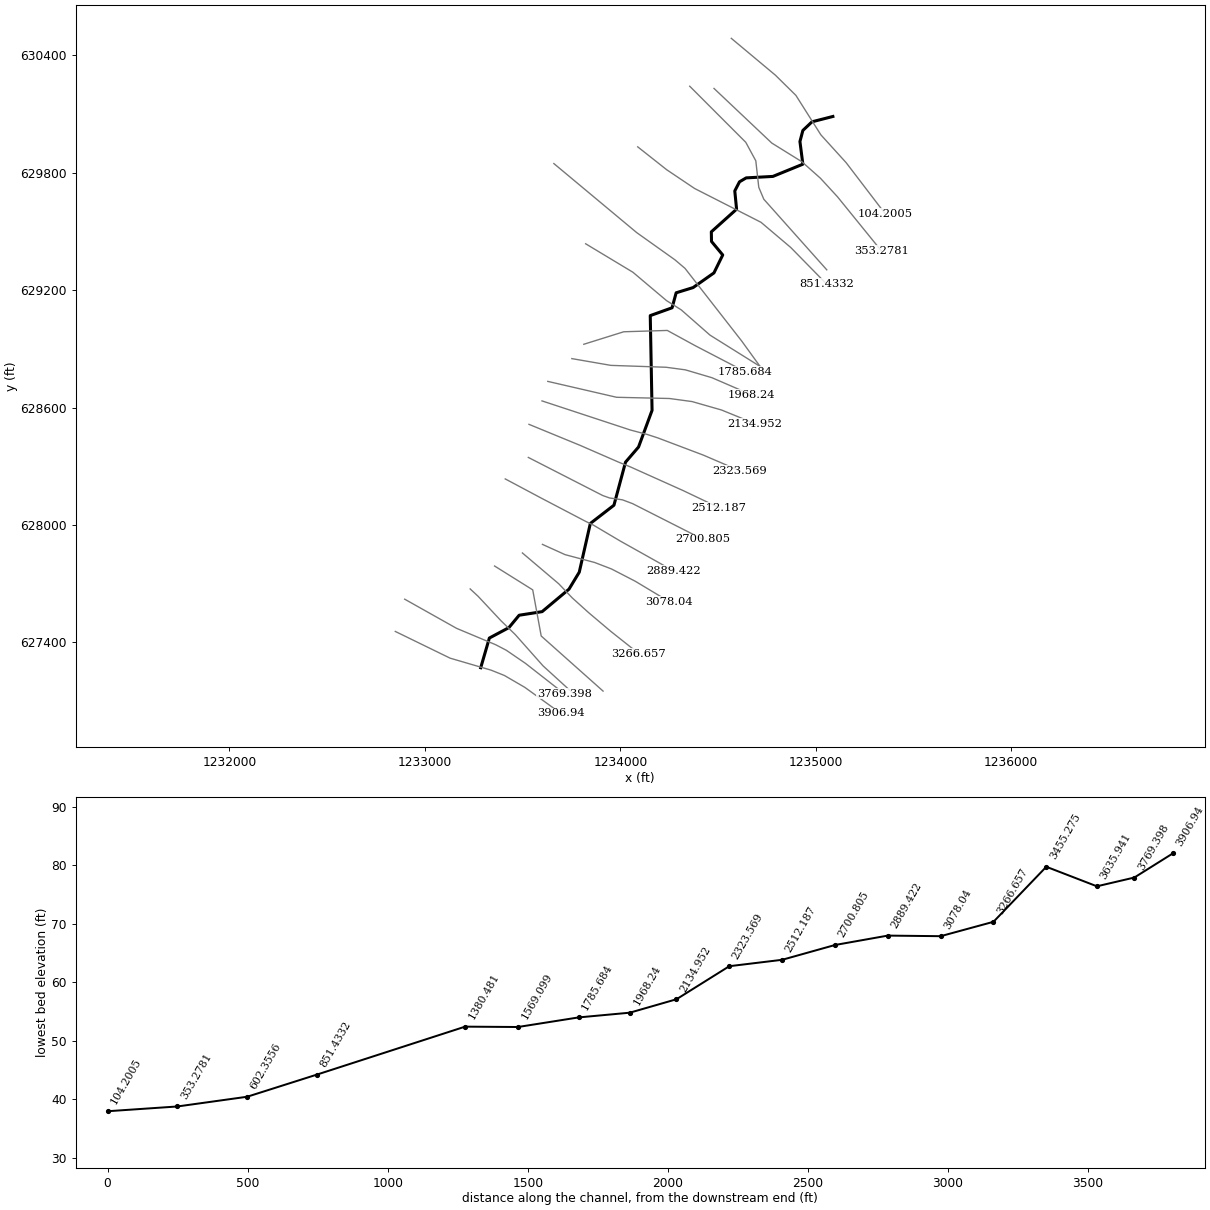
--- 686_ras.prj (project) ---

Proj Title=686
Current Plan=p01
Default Exp/Contr=0.3,0.1
English Units
Geom File=g01
Flow File=f01
Plan File=p01
Y Axis Title=Elevation
X Axis Title(PF)=Main Channel Distance
X Axis Title(XS)=Station
BEGIN DESCRIPTION:
RFD model 686 exported to HEC-RAS
END DESCRIPTION:

--- 686_ras.p01 (plan) ---

Plan Title=Plan 01
Program Version=4.10
Short Identifier=Plan 01
Geom File=g01
Flow File=f01
Subcritical Flow
Calc Critical at every XS
Secant Critical Depth

--- 686_ras.f01 (steady flow) ---

Flow Title=Flow 01
Program Version=5.01
Number of Profiles= 5
Profile Names=10yr,25yr,50yr,100yr,500yr
River Rch & RM=686,19, 3906.94
  797.96 1059.35 1293.97 1537.98 2072.07
River Rch & RM=686,19,3769.398
  798.83 1060.67 1295.63 1540.19 2075.47
River Rch & RM=686,19,3635.941
  803.12  1067.2 1303.84 1551.19 2092.42
River Rch & RM=686,19,3455.275
  812.45 1081.42 1321.72 1575.14  2129.4
River Rch & RM=686,19,3266.657
  816.08 1086.96 1328.68 1584.49 2143.84
River Rch & RM=686,19, 3078.04
  819.68 1092.46 1335.61 1593.78 2158.22
River Rch & RM=686,19,2889.422
  820.79 1094.15 1337.73 1596.63 2162.64
River Rch & RM=686,19,2700.805
  824.91 1100.45 1345.66 1607.28 2179.13
River Rch & RM=686,19,2512.187
  879.82 1184.81 1451.91 1750.81 2402.92
River Rch & RM=686,19,2323.569
  889.16 1199.24 1470.12 1775.53 2441.74
River Rch & RM=686,19,2134.952
  901.47 1218.29 1494.15 1808.23 2493.21
River Rch & RM=686,19, 1968.24
  902.43 1219.77 1496.02 1810.78 2497.22
River Rch & RM=686,19,1785.684
  904.33 1222.72 1499.74 1815.85 2505.22
River Rch & RM=686,19,1569.099
  911.19 1233.35 1513.16 1834.14 2534.07
Boundary for River Rch & Prof#=686,19,1
Up Type= 0
Dn Type= 2
Boundary for River Rch & Prof#=686,19,2
Up Type= 0
Dn Type= 2
Boundary for River Rch & Prof#=686,19,2
Up Type= 0
Dn Type= 2
Boundary for River Rch & Prof#=686,19,2
Up Type= 0
Dn Type= 2
Boundary for River Rch & Prof#=686,19,2
Up Type= 0
Dn Type= 2

--- 686_ras.g01 (geometry) ---

Geom Title=686
Program Version=4.10

River Reach=686,19
Reach XY= 30
1233285.58719402627269.705867182 1233329.7514511627421.397815564
1233429.75142313627474.7311301341233482.25140949 627538.06444314
1233599.75137537627556.3977676391233737.25133813627671.397729504
1233789.75132516627758.0643689081233846.41798236628007.230959964
1233967.25128275 628100.564262081234026.41793837628320.564195051
 1234093.0845876628398.0641701191234162.25123933 628585.56411243
1234153.03219515629069.9133684441234264.69883001629109.913353314
 1234285.5321595629186.579996605 1234372.1988013629213.246652854
1234478.86543875629288.2466274981234523.86542814629379.913265623
1234466.36544713 629449.079913431234465.53211547629498.246565526
1234594.69874738 629614.079860721234585.53208614629707.413166591
1234609.69874704629754.0798187461234643.86540421 629774.07981179
1234780.53203076629781.5798055921234933.86532067629844.079782583
1234918.86532848629959.9130819591234933.86532568 630016.57973137
1234980.53197986630060.7463835841235087.44891532630088.052027807

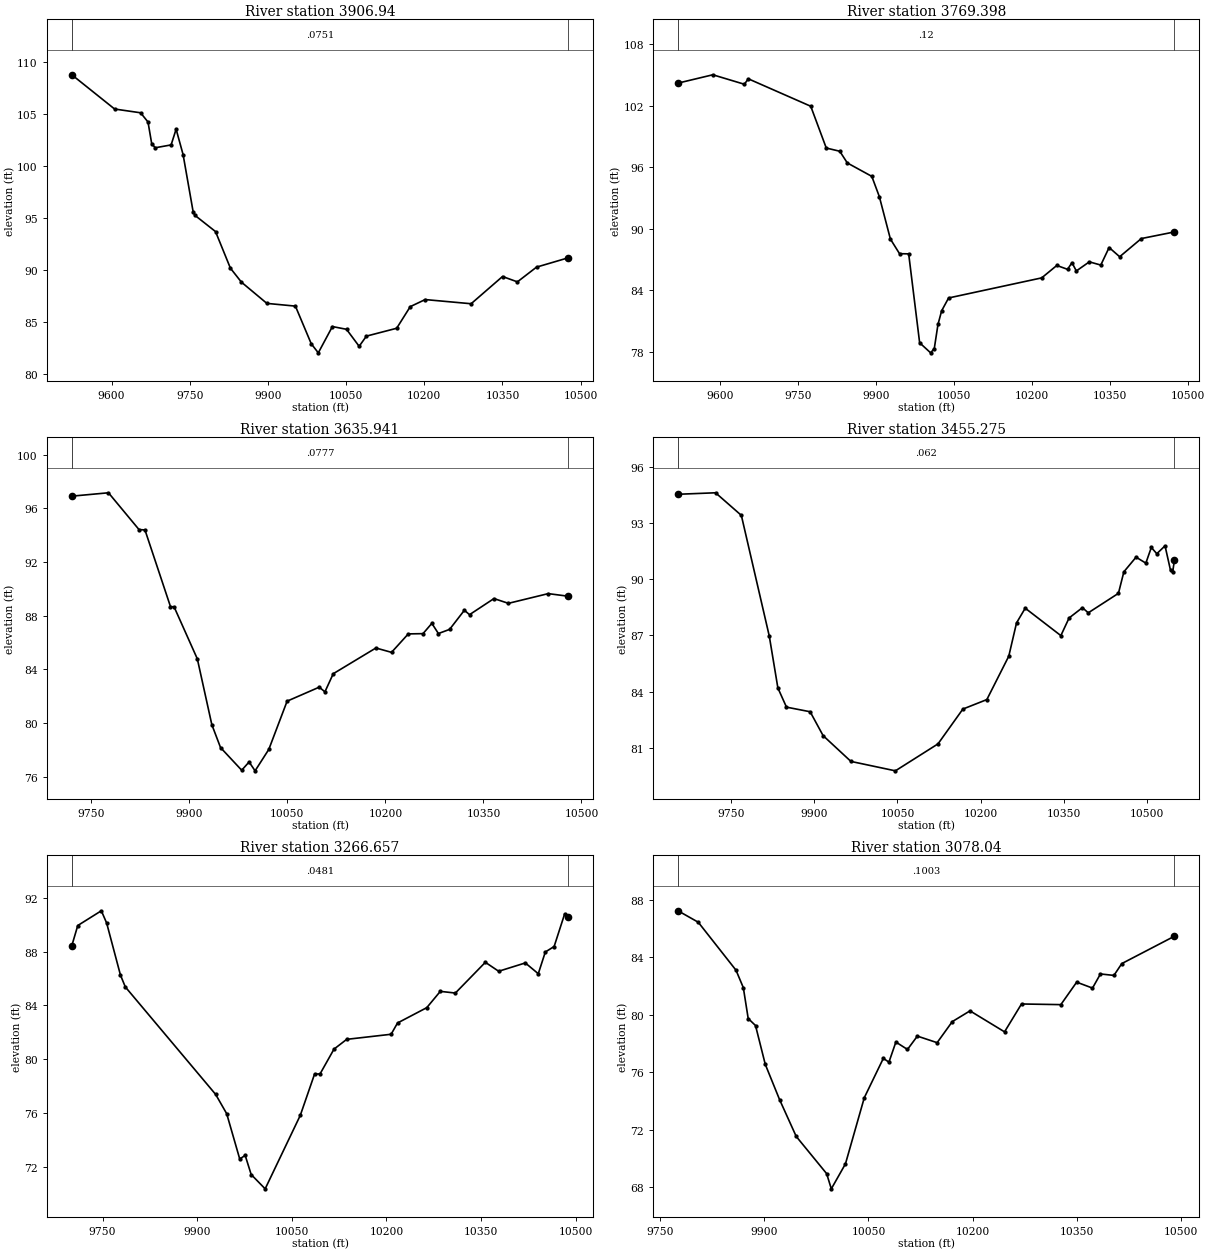
Type RM Length L Ch R = 1 , 3906.94,137.542400,137.542400,137.542400
XS GIS Cut Line= 6
1232848.46656864627455.2100979611233128.95497176627318.579493736
1233339.00323567627257.1531138631233406.95283428627229.971669409
1233511.15905295627169.3050985281233695.71062019627036.293221773
#Sta/Elev= 30
 9523.67108.81689605.822105.52189655.665105.15979669.905104.27359677.026102.1821
9683.792101.79349714.242102.06779723.863103.58229737.235101.13969756.535 95.6333
9760.22895.281519799.49593.728849828.04290.207549849.20688.861279898.05186.81871
9952.79586.556589983.19382.931159996.70482.0608810023.7684.5903310050.8584.32558
 10075.182.6893410089.0583.66902 10147.184.4256910173.1886.5058910201.7887.18657
10289.9886.7854310350.2589.4055710378.78 88.890110415.4790.3074110476.3191.20503
#Mann= 3 , 0 , 0
 9523.67  0.0751       0 9523.67  0.0751       010476.31  0.0751       0
#XS Ineff= 2 , 0
       0                               0
Bank Sta=9523.67,10476.31
Exp/Cntr=0.3,0.1

Type RM Length L Ch R = 1 ,3769.398,133.456800,133.456800,133.456800
XS GIS Cut Line= 6
1232896.58111194627620.1159977861233162.07955596627470.999320004
1233363.00355652627386.878114665 1233416.6229262627358.874408551
1233514.59389906627291.9307766611233713.22755768627136.653470766
#Sta/Elev= 30
 9519.75104.18479586.621104.99689647.241104.07469654.818104.60439774.783101.9334
9804.61997.865549830.538 97.55339845.02296.414669892.09595.108339906.57993.13642
9927.84389.004219945.39787.580269962.95287.564149984.01778.9081110005.1277.92843
10012.1878.3494910019.2480.68919 10026.382.0215210039.6683.2695310218.5585.22594
 10247.686.4355410268.1786.0576610276.7586.7055510285.0885.8989410310.07 86.7866
 10332.186.4729510348.0888.1819910368.3787.2831210410.0189.0534710473.5889.69809
#Mann= 3 , 0 , 0
 9519.75    0.12       0 9519.75    0.12       010473.58    0.12       0
#XS Ineff= 2 , 0
       0                               0
Bank Sta=9519.75,10473.58
Exp/Cntr=0.3,0.1

Type RM Length L Ch R = 1 ,3635.941,180.666100,180.666100,180.666100
XS GIS Cut Line= 6
1233231.62463818627672.5366428751233271.90668892627635.195868721
1233390.16877882627508.9722862391233462.02012729 627439.49623219
1233604.32724853627279.3363797451233764.94091617627132.906493765
#Sta/Elev= 30
9720.11296.898549776.21397.150749822.87794.413219832.07994.379099871.06788.67605
9876.70788.642459912.20584.772819934.39179.870799947.70278.165649980.07276.47615
9991.41877.0921610000.5776.43073 10021.678.0299910049.5881.62305 10098.882.66718
10107.4482.3161510120.1883.6674610185.4385.5844510209.3785.26001   1023586.63437
10257.5386.6540610271.0887.4202710281.0886.6611810298.2386.9711510320.8588.39747
10328.7288.06696 10366.1 89.266910388.2588.9124510449.1789.6358310479.7489.44288
#Mann= 3 , 0 , 0
9720.112  0.0777       09720.112  0.0777       010479.74  0.0777       0
#XS Ineff= 2 , 0
       0                               0
Bank Sta=9720.112,10479.74
Exp/Cntr=0.3,0.1

Type RM Length L Ch R = 1 ,3455.275,188.617600,188.617600,188.617600
XS GIS Cut Line= 4
1233356.48922643627789.7161807271233551.66581827627667.730810851
1233595.03839421627431.8924290391233911.58426824627150.210801542
#Sta/Elev= 30
9655.04294.529979722.63294.609489769.05993.404229819.35486.96353 9834.8384.19616
9850.30683.173189892.92382.927289916.27481.652619966.31280.2776710046.3779.77483
 10123.181.2133210167.8683.0696710211.0283.57623 10250.585.8906810264.48  87.668
10280.1288.4525910344.2786.9890610359.0887.9303510383.0588.4807810393.6388.20532
10447.92 89.244610457.7190.3930410479.6791.1745710497.27 90.855810507.1491.69335
10517.0191.3576910531.8291.7797610541.6990.4736210545.5590.3732310548.7391.02013
#Mann= 3 , 0 , 0
9655.042   0.062       09655.042   0.062       010548.73   0.062       0
#XS Ineff= 2 , 0
       0                               0
Bank Sta=9655.042,10548.73
Exp/Cntr=0.3,0.1

Type RM Length L Ch R = 1 ,3266.657,188.617700,188.617700,188.617700
XS GIS Cut Line= 6
1233498.83013862627856.3887899461233684.88597183627698.743055184
1233754.02272915627626.5838482821233838.77696054627550.337430622
1233950.62994103627455.9525750861234094.04532279627342.303664185
#Sta/Elev= 30
 9701.1788.443669710.63489.947759747.99691.045369756.44690.131759778.33686.26082
9786.01785.381029929.29977.381269946.78375.948159967.46472.578419976.12872.84203
 9985.6371.42009 10007.8 70.355310063.54 75.826910086.0878.8853810094.9178.91232
10116.98 80.752610137.1281.4789810207.5381.8567810217.7182.6959610264.0883.83664
10285.5485.0495510309.4384.9238210356.9787.21173 10378.186.5449210420.3687.16444
10440.9286.3617210452.06 87.977910466.0488.3867710482.7890.8176310488.3890.55431
#Mann= 3 , 0 , 0
 9701.17  0.0481       0 9701.17  0.0481       010488.38  0.0481       0
#XS Ineff= 2 , 0
       0                               0
Bank Sta=9701.17,10488.38
Exp/Cntr=0.3,0.1

Type RM Length L Ch R = 1 , 3078.04,188.617600,188.617600,188.617600
XS GIS Cut Line= 6
1233601.32219457627900.3139567851233717.58088739627847.711908231
1233868.32764428627807.8051831241233954.51472548 627774.70081167
1234076.42410449627711.7683250731234249.41956837627608.009090349
#Sta/Elev= 30
 9775.69 87.23149804.868 86.43379859.24183.097669869.776 81.88459876.79979.73777
9887.33479.249819901.38176.551749921.99474.097039945.96971.537179989.77768.95037
9996.517 67.892310016.8969.6295110044.0474.2325610071.4776.9679810079.5276.70316
10089.5278.1014810106.2477.5857210120.4778.5143410148.9478.0583110170.77 79.5219
10196.3380.2703710246.0678.8103810270.4980.7495710327.1680.7039410349.9682.26677
10372.7681.8540210384.2182.8376210403.5982.7357710414.9983.5590910490.7885.46216
#Mann= 3 , 0 , 0
 9775.69  0.1003       0 9775.69  0.1003       010490.78  0.1003       0
#XS Ineff= 2 , 0
       0                               0
Bank Sta=9775.69,10490.78
Exp/Cntr=0.3,0.1

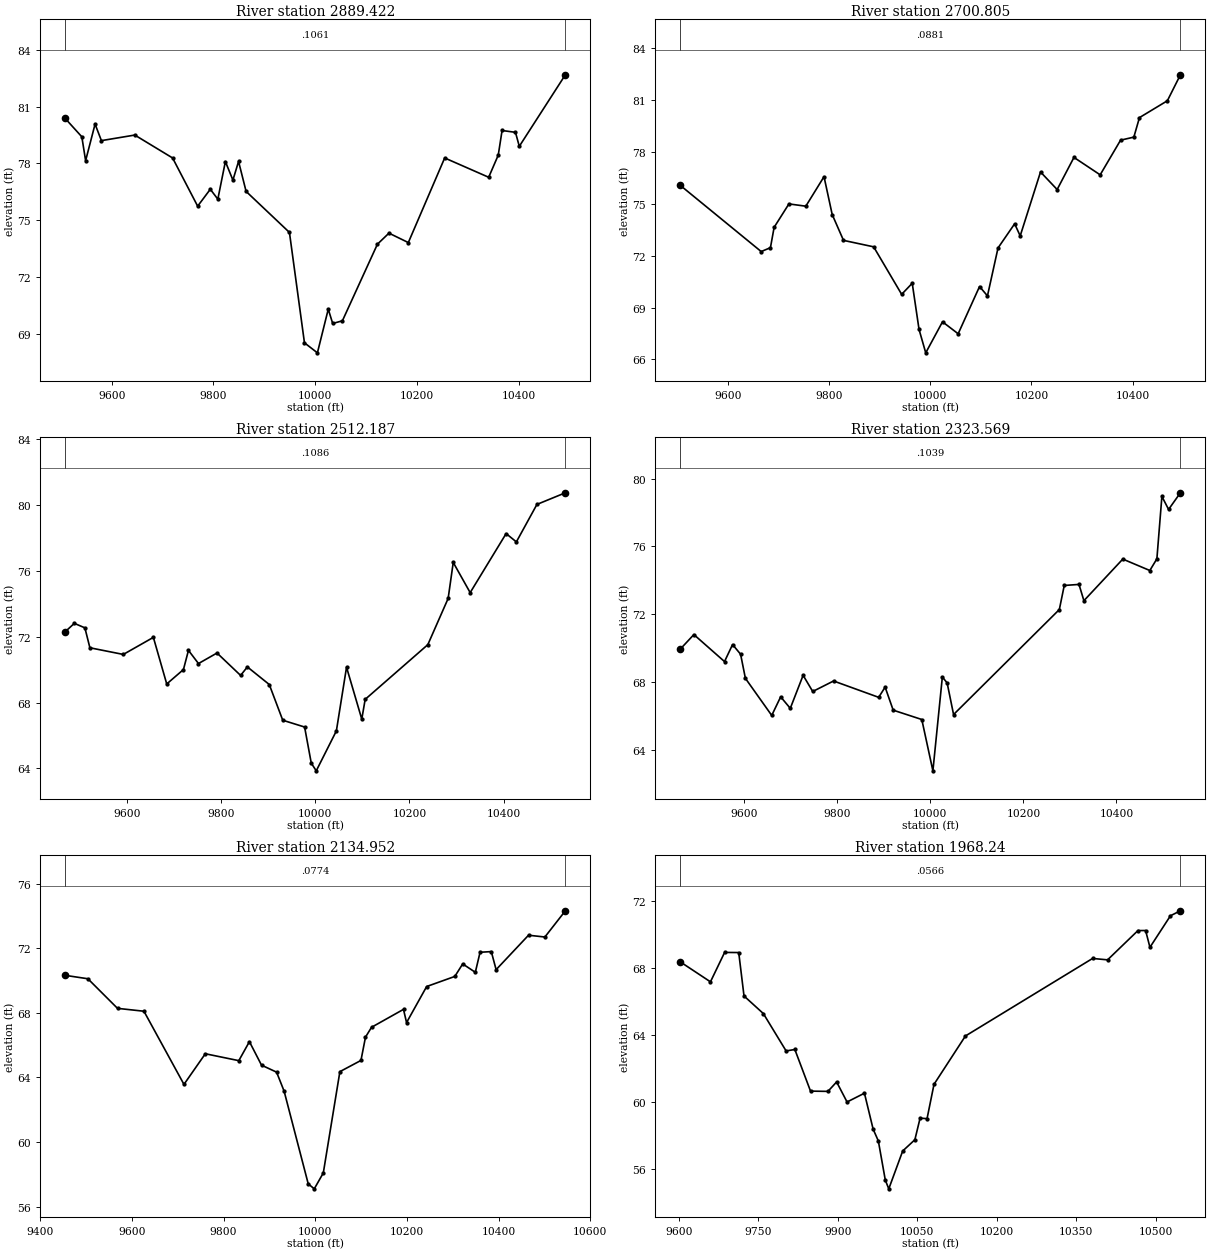
Type RM Length L Ch R = 1 ,2889.422,188.617600,188.617600,188.617600
XS GIS Cut Line= 6
1233411.05530258628234.9833573771233596.44862458628136.280482267
1233819.75944444628019.405495412 1233864.0211164627997.682368508
1234000.33658653627916.9689742231234273.64166926627763.965024115
#Sta/Elev= 30
9508.45380.378529541.30379.404929548.736 78.14369567.321 80.07649579.75379.20295
9645.37479.497369719.70678.285839768.91875.740589793.76676.634179808.57876.11125
9823.39178.098039838.20377.117389849.31278.104199864.12476.519899949.29374.35356
9978.80768.5221310004.2567.9930610025.5970.2996710034.2969.5441210053.3669.68463
10122.1873.7317310144.8674.3157610182.9373.8177410254.3778.2871210340.8577.26735
10359.6578.4361710367.1779.7380210393.4979.6413510401.0178.9013610491.5482.68129
#Mann= 3 , 0 , 0
9508.453  0.1061       09508.453  0.1061       010491.54  0.1061       0
#XS Ineff= 2 , 0
       0                               0
Bank Sta=9508.453,10491.54
Exp/Cntr=0.3,0.1

Type RM Length L Ch R = 1 ,2700.805,188.617700,188.617700,188.617700
XS GIS Cut Line= 6
1233529.14261261628344.8672614851233910.10260976628149.949531735
1233945.46917739 628137.429820091234010.36659889 628128.24985992
1234062.56751479628108.6409773531234420.62412902627927.137072926
#Sta/Elev= 30
9505.77876.077589665.90672.242089684.16672.466359691.47173.645519720.68874.99833
9754.07274.866459790.053  76.5749806.19374.38477 9828.5372.888929888.09672.51571
9943.45569.766819964.34970.407929977.79867.736049991.02666.3828610024.1568.17755
 10055.167.4859210097.34 70.219910112.9769.6773610133.8572.4502810166.7173.84901
10177.6673.1477410217.8276.8460710250.68  75.83110283.9177.6887110335.6776.68059
10375.9878.6852710402.2378.8626910413.3279.9914810468.4780.9659910494.2282.46893
#Mann= 3 , 0 , 0
9505.778  0.0881       09505.778  0.0881       010494.22  0.0881       0
#XS Ineff= 2 , 0
       09782.334                       0
Bank Sta=9505.778,10494.22
Exp/Cntr=0.3,0.1

Type RM Length L Ch R = 1 ,2512.187,188.617600,188.617600,188.617600
XS GIS Cut Line= 6
1233532.46602986628514.0163333551233793.56983569 628406.79464793
1233992.85203323628320.0399901111234051.15852782628296.515439773
1234321.84509352628175.0931445371234505.07039185628087.876067729
#Sta/Elev= 30
9468.95672.304669488.497 72.81859510.92172.545969521.56171.333949592.49570.92864
9656.33571.966639684.70969.132869720.17670.008849730.81671.176569752.10470.37415
9791.46471.01552 9841.5669.651929855.87370.17041 9902.3969.099929931.01666.92807
9977.42266.514249991.55864.3190510002.1463.8502310044.8766.2788810066.4470.15057
10098.8166.99322   1010668.1959110239.0471.5232910282.1974.3356810292.9876.52223
10328.9474.6869510405.2578.2765310427.0377.7721410470.6580.0504510531.0480.75921
#Mann= 3 , 0 , 0
9468.956  0.1086       09468.956  0.1086       010531.04  0.1086       0
#XS Ineff= 2 , 0
       09923.092                       0
Bank Sta=9468.956,10531.04
Exp/Cntr=0.3,0.1

Type RM Length L Ch R = 1 ,2323.569,188.617700,188.617700,188.617700
XS GIS Cut Line= 6
1233599.12657943628633.8431185981234052.21340657628484.788126052
1234138.25150665628462.0958675571234192.72688955628444.320151626
1234424.56318434628356.7239782381234611.54212188628276.460530684
#Sta/Elev= 30
9462.69769.931079492.18670.797599557.99669.204559575.29770.208889592.517  69.638
9602.84968.215129659.42466.025899678.61567.122919699.27866.443669726.82968.39341
9747.49367.438119792.26468.058349889.151 67.09349903.00967.695589920.33366.33632
9981.79665.7848310005.63 62.755210025.9368.2928310036.23 67.944210050.0366.07799
10277.2472.27532 10287.873.6965610319.4673.7575110330.0272.7970410413.57 75.2528
10471.6174.5791410486.7875.2668410497.5578.9502910511.9578.1843710537.31 79.1666
#Mann= 3 , 0 , 0
9462.697  0.1039       09462.697  0.1039       010537.31  0.1039       0
#XS Ineff= 2 , 0
       0 9922.62                       0
Bank Sta=9462.697,10537.31
Exp/Cntr=0.3,0.1

Type RM Length L Ch R = 1 ,2134.952,166.711400,166.711400,166.711400
XS GIS Cut Line= 6
1233628.69499023628733.6290281331233980.83758586628652.343708361
1234251.08604376628646.1514275611234366.98624756628630.435686389
1234517.68442348628587.3402198521234688.45027501628517.692941783
#Sta/Elev= 30
 9454.4370.320739504.07970.10882 9568.7168.275799626.33368.097739713.65263.56662
9760.23165.463879833.28565.036539856.40466.213479882.82664.757419915.69964.32393
9932.13463.144239984.68857.406229997.847 57.097610017.58 58.081410053.7264.35582
 10099.765.0497910109.5966.4944710122.7767.1030810192.49 68.213610199.15  67.395
10242.99 69.6274 10304.470.2526710321.6171.0276810349.1570.5084510359.47 71.7491
10383.9971.7914810394.5170.6725510465.1672.8043510500.8672.6946310545.5474.31893
#Mann= 3 , 0 , 0
 9454.43  0.0774       0 9454.43  0.0774       010545.54  0.0774       0
#XS Ineff= 2 , 0
       09833.818                       0
Bank Sta=9454.43,10545.54
Exp/Cntr=0.3,0.1

Type RM Length L Ch R = 1 , 1968.24,182.556500,182.556500,182.556500
XS GIS Cut Line= 6
1233751.70732526628850.1079534131233951.62133508628815.496707886
1234234.14773006628805.8741976491234332.53162138628792.669564883
1234468.69146992628752.4620257931234667.73171104628666.353589374
#Sta/Elev= 30
9602.64468.35107 9659.8367.154659686.54168.910159713.181 68.90279723.17166.30951
9759.68865.258999802.63663.027749819.09363.11648 9848.6960.630529881.53960.61496
9897.94661.178349917.634 59.98219950.44860.506079966.85558.360799976.69957.65533
9989.82555.319699996.387 54.797110022.6557.0564410045.6357.7283710055.4859.01738
10068.61 58.986710081.7461.0365610141.06 63.922410381.0368.5504710409.3368.46674
10466.6470.2143910481.0870.2178210489.2869.2154610528.0171.0992710546.7771.39617
#Mann= 3 , 0 , 0
9602.644  0.0566       09602.644  0.0566       010546.77  0.0566       0
#XS Ineff= 2 , 0
       09793.479                       0
Bank Sta=9602.644,10546.77
Exp/Cntr=0.3,0.1

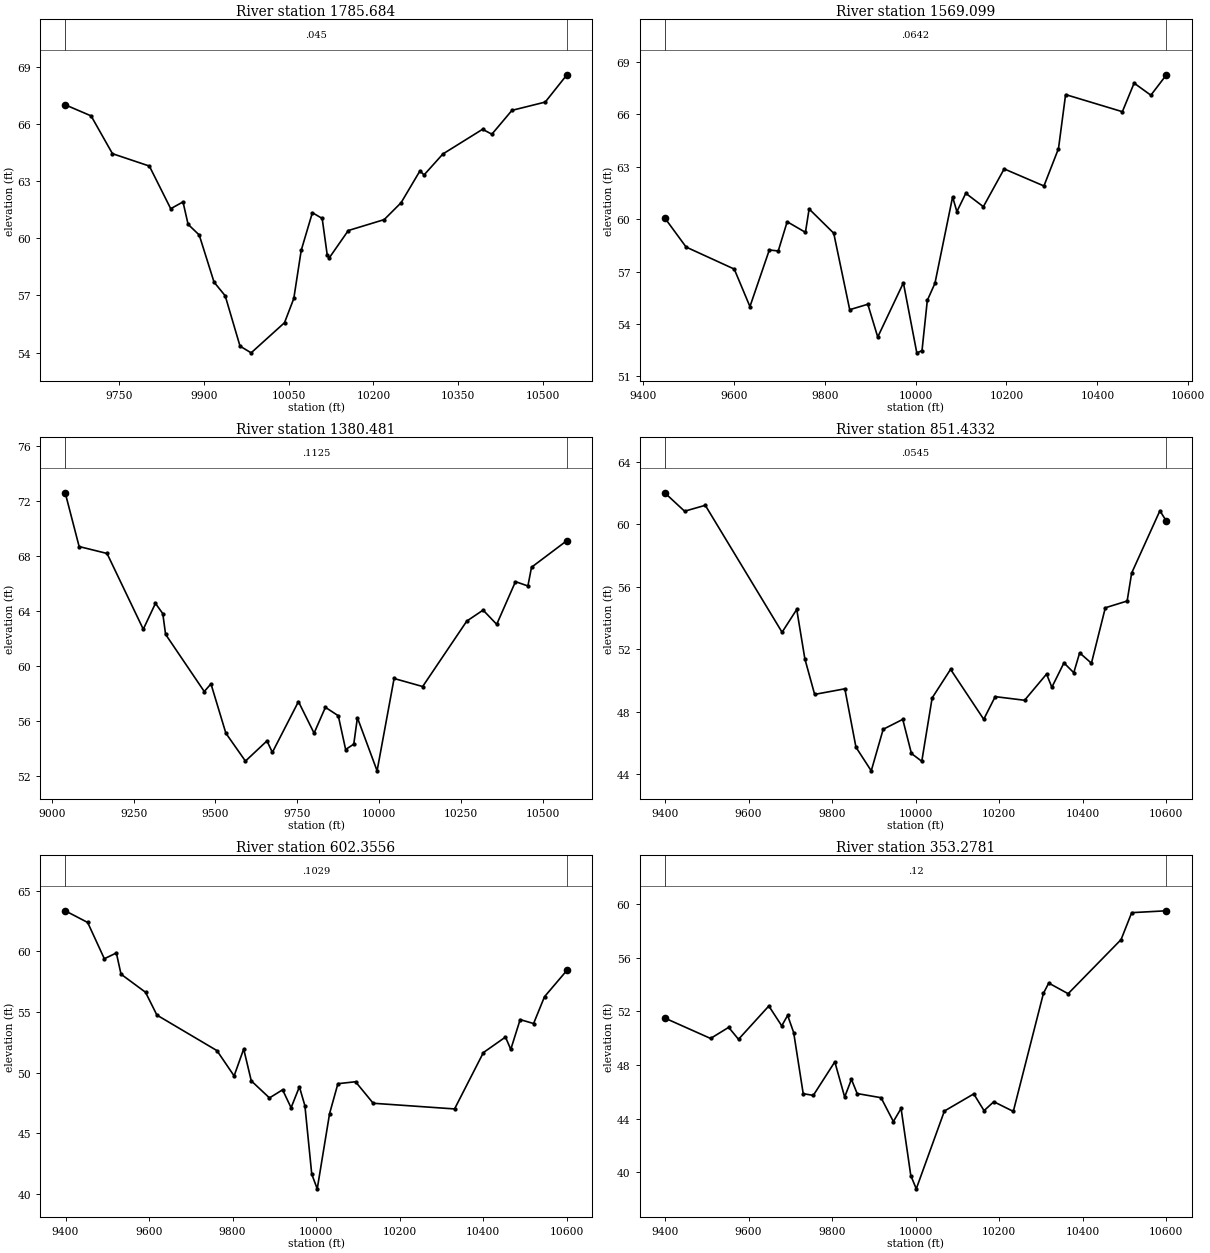
Type RM Length L Ch R = 1 ,1785.684,216.585000,216.585000,216.585000
XS GIS Cut Line= 5
1233812.97231883628923.3997429611234017.50080645628987.314895347
1234240.17258603628994.124260814 1234382.5997557628916.363039269
1234638.80088432628783.269711279
#Sta/Elev= 30
9654.41667.007489700.24866.425799738.05864.442299803.36763.792639841.17761.55498
9862.93361.909799871.95960.733369891.65360.173539917.91257.698359937.60656.98362
9963.86554.341349983.55953.9892410042.6455.5723310059.0556.8437710072.1859.37025
10091.9361.3444610109.2761.04424 10118.159.1475410121.8458.9750210155.48  60.408
10219.0260.9814710248.9361.8677110282.2563.5354510289.6563.3286210322.9264.42671
10393.17 65.722510409.5965.4633110445.1866.7154210504.08 67.150410542.4668.58303
#Mann= 3 , 0 , 0
9654.416   0.045       09654.416   0.045       010542.46   0.045       0
#XS Ineff= 2 , 0
       0                               0
Bank Sta=9654.416,10542.46
Exp/Cntr=0.3,0.1

Type RM Length L Ch R = 1 ,1569.099,188.617600,188.617600,188.617600
XS GIS Cut Line= 6
1233822.46289872629437.1833607871234064.18202033629291.717042336
1234236.39662834629146.472616604 1234311.1754465629099.575877964
1234458.75668418628970.1397435581234722.89635251628805.117167696
#Sta/Elev= 30
9447.92760.075959494.99958.405289600.94357.143939635.47254.996519678.12458.23846
9697.77258.17925 9717.42 59.85429757.60459.246899765.72560.585899819.85559.19784
9855.04354.819069894.88255.129239916.71853.252939973.16656.3550510002.6852.34844
10014.1252.4727310025.8255.3509310042.6156.3300310081.48 61.276210090.8960.43354
10110.4861.4819810149.1560.7158610194.9462.8788110282.4861.9018610314.4964.03985
10330.1467.1343210455.0766.1538310480.9267.7900110517.7767.0980210552.0868.26749
#Mann= 3 , 0 , 0
9447.927  0.0642       09447.927  0.0642       010552.08  0.0642       0
#XS Ineff= 2 , 0
       09764.961                       0
Bank Sta=9447.927,10552.08
Exp/Cntr=0.3,0.1

Type RM Length L Ch R = 1 ,1380.481,529.047900,529.047900,529.047900
XS GIS Cut Line= 6
1233659.85634999629847.2820082081234083.53433032629494.409327708
1234279.13242377629355.3544510821234330.98508681629311.329244591
1234621.25134255628939.4948635621234739.58844198628775.966674454
#Sta/Elev= 30
9040.75972.593079083.37968.690049168.58968.188259279.36362.689119316.61864.56676
9339.01163.822579347.53262.318149465.75258.166739486.23558.722629531.81555.14018
9591.57253.116049657.396 54.58389673.84653.747799753.59957.434179801.34955.14492
9835.959 57.02099875.362  56.4079897.78953.958449922.65454.34768 9933.74 56.2671
9993.90552.4095610045.8559.1125410133.1458.5287910267.9963.2794510317.88 64.0765
10359.4663.0436810416.8266.1442610454.7765.8274910465.81 67.186210574.0269.12094
#Mann= 3 , 0 , 0
9040.759  0.1125       09040.759  0.1125       010574.02  0.1125       0
#XS Ineff= 2 , 0
       09833.233                       0
Bank Sta=9040.759,10574.02
Exp/Cntr=0.3,0.1

Type RM Length L Ch R = 1 ,851.4332,249.077600,249.077600,249.077600
XS GIS Cut Line= 6
1234088.82813989629932.7906901721234237.22319717629815.659435204
1234380.10641818 629719.767470711234719.78887746629546.921735586
1234871.97728946629418.1173788181235053.22706839 629233.38315696
#Sta/Elev= 30
9399.06262.028619446.67860.846549496.23461.225829680.18253.087129715.28754.55124
9734.79151.380639758.19449.104279830.537 49.46229857.17345.717749893.78844.20378
 9922.3746.86708 9969.2647.50259 9990.0545.3162810014.8244.8142510039.6648.87736
10083.8150.7104810163.2447.5070710190.6948.9603110261.0648.7279110313.7350.40794
10326.4249.5621310355.3851.1242910378.8950.49398   10393 51.766210421.2251.10381
10454.4754.6564610506.7755.0904610517.57 56.882510585.2460.8766310600.9260.20209
#Mann= 3 , 0 , 0
9399.062  0.0545       09399.062  0.0545       010600.92  0.0545       0
#XS Ineff= 2 , 0
       0                               0
Bank Sta=9399.062,10600.92
Exp/Cntr=0.3,0.1

Type RM Length L Ch R = 1 ,602.3556,249.077500,249.077500,249.077500
XS GIS Cut Line= 6
1234354.97775955630242.6592742431234641.85595231629955.857011778
1234693.09586547629861.3076985581234708.24978674629725.968697525
 1234733.9958195 629664.972512631235056.23257671629303.961213289
#Sta/Elev= 30
9399.11363.337429452.94362.373499492.88359.382949521.66859.859489532.823  58.111
9591.49356.62013  9618.854.736989762.56551.808489803.71649.721939826.63151.93951
9844.82349.314389888.37947.908029919.80148.577649940.16347.097919960.08748.82404
9973.24547.263259989.66341.62057 10002.840.4111610032.3946.6173210052.2949.08009
10094.5449.2412610136.8647.4674410331.7246.9992810400.7751.6467410453.6652.92585
10466.3651.90751 10488.854.3655210520.9754.0400510547.1556.2524110600.8458.42592
#Mann= 3 , 0 , 0
9399.113  0.1029       09399.113  0.1029       010600.84  0.1029       0
#XS Ineff= 2 , 0
       0                               0
Bank Sta=9399.113,10600.84
Exp/Cntr=0.3,0.1

Type RM Length L Ch R = 1 ,353.2781,249.077600,249.077600,249.077600
XS GIS Cut Line= 6
1234479.13991327630231.4433176071234774.91869852629952.035870227
1234928.61248277629856.7742462031235023.80026911629772.245763491
1235110.93503642629677.4572454541235336.35345134629399.891824969
#Sta/Elev= 30
9399.06351.50935 9508.9149.98201 9552.2850.812389575.81649.918099648.47352.40842
9679.37450.924079693.49651.705039707.95150.426799730.827 45.8554 9754.9845.72858
 9806.5448.232829830.13245.606299846.33246.929829860.03245.86599 9917.2645.55542
  9946.843.773729965.26344.754729988.51539.7415210001.6538.7468910069.0144.55882
10139.3445.8398210163.9944.5875610187.3745.2551710234.1144.5320910306.27 53.3539
10318.9554.1198910365.4453.3263510492.2357.3672610517.7159.3803310600.9559.52098
#Mann= 3 , 0 , 0
9399.063    0.12       09399.063    0.12       010600.95    0.12       0
#XS Ineff= 2 , 0
       0                               0
Bank Sta=9399.063,10600.95
Exp/Cntr=0.3,0.1

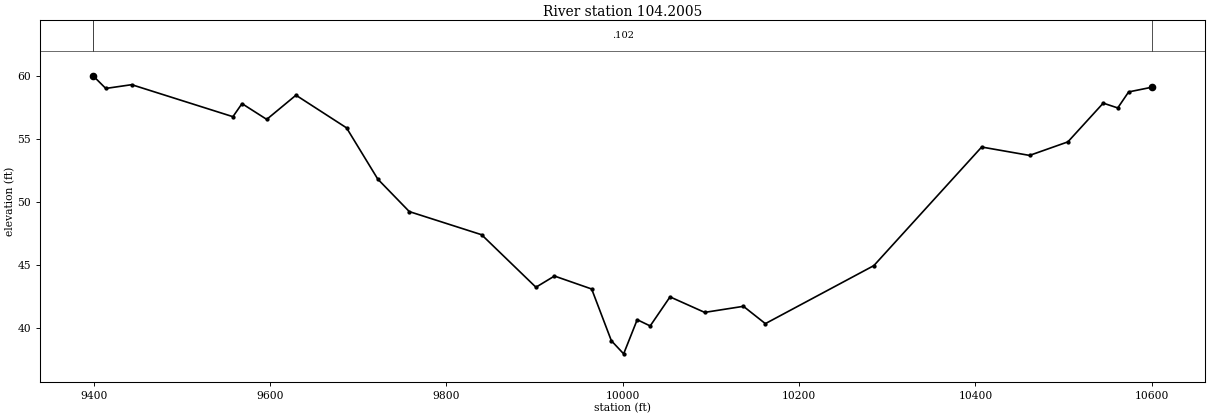
Type RM Length L Ch R = 1 ,104.2005,0.000000,0.000000,0.000000
XS GIS Cut Line= 6
1234567.67699664630487.5408106011234793.21781577630299.283502806
1234898.13724862630196.0220749611235026.03454711629994.082561339
1235155.29269209629851.8386906811235354.94064977629590.694949623
#Sta/Elev= 30
9399.06560.01628 9413.46 59.0105 9442.8959.309159557.71656.767099568.021 57.8054
9596.07556.552379629.24758.473739686.62255.879779722.12651.804729757.84949.22888
9839.86847.391059901.48443.221299922.51744.110779964.72143.080739987.05938.97224
   1000137.9311610016.3940.64312 10031.140.1462710053.6242.4553610092.9341.22329
10136.8941.7053410161.7740.3296710284.8544.9377110407.1754.35747 10461.553.69118
10504.9754.7661310545.0957.8448910561.5557.46189 10573.958.7331210600.9259.11687
#Mann= 3 , 0 , 0
9399.065   0.102       09399.065   0.102       010600.92   0.102       0
#XS Ineff= 2 , 0
       0                               0
Bank Sta=9399.065,10600.92
Exp/Cntr=0.3,0.1